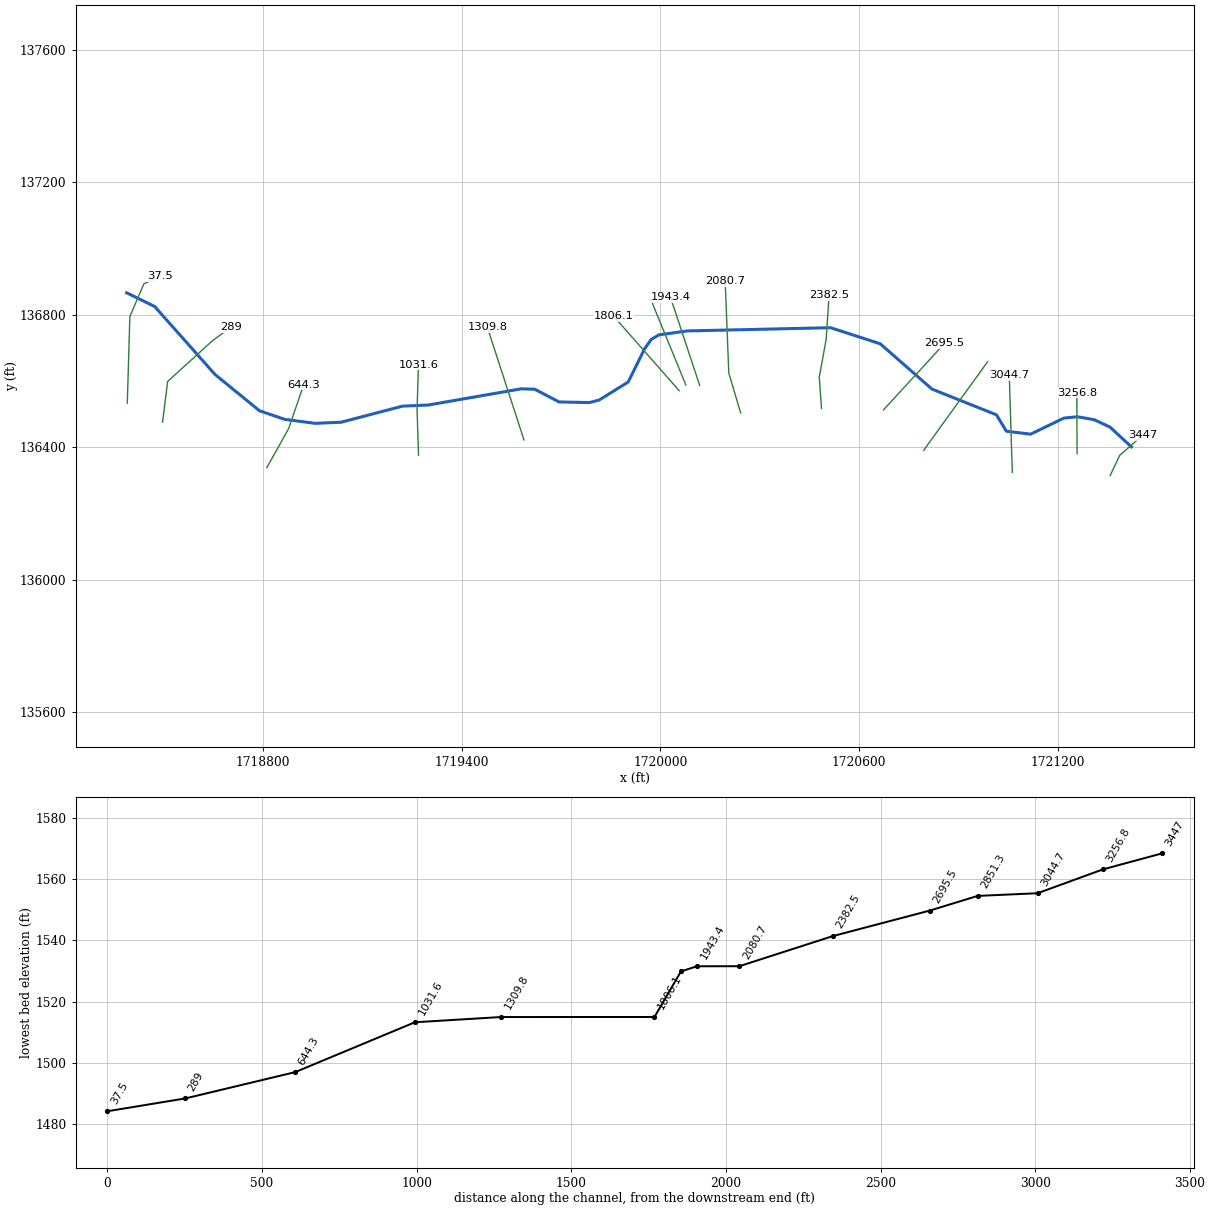
--- Birchlick Branch.prj (project) ---

Proj Title=Birchlick Branch
Current Plan=p01
Default Exp/Contr=0,0
English Units
Geom File=g01
Flow File=f01
Plan File=p01
BEGIN DESCRIPTION:
END DESCRIPTION:
DSS Export Rating Curves= 0
DSS Export Rating Curve Sorted= 0
DSS Export Volume Flow Curves= 0
DXF OffsetX= 0
DXF OffsetY= 0
DXF ScaleX= 0
DXF ScaleY= 0

--- Birchlick Branch.p01 (plan) ---

Plan Title=Floodplain
Program Version=4.00
Geom File=g01
Flow File=f01
K Sum by GR=0
Std Step Tol=0.01
Critical Tol=0.01
Num of Std Step Trials=20
Max Error Tol=0.3
Flow Tol Ratio=0.001
Split Flow NTrial=30
Split Flow Tol=0.02
Split Flow Ratio=0.02
Log Output Level=0
Friction Slope Method=1
Unsteady Friction Slope Method=2
Unsteady Bridges Friction Slope Method=1
Global Log Level=0
CheckData=False
Run HTab=0
Run UNet=0
Run PostProcess=0
UNET Theta=0
UNET Theta Warmup=0
UNET ZTol=0
UNET ZSATol=0
UNET MxIter=0
UNET MaxInSteps=0
UNET DtIC=0
UNET DtMin=0
UNET MaxCRTS=0
UNET WFStab=0
UNET SFStab=0
UNET WFX=0
UNET SFX=0
UNET DSS MLevel=0
UNET DZMax Abort=0
UNET Convert EG Bridges=0
UNET Use Existing IB Tables=0
UNET Froude Limit=0
UNET Froude Power=0
Write IC File=0
Echo Input=False
Echo Output=False
Write Detailed=0

--- Birchlick Branch.f01 (steady flow) ---

Flow Title=NFF Regression Equation
Program Version=4.00
Number of Profiles=1
Profile Names=P100yr
River Rch & RM=Birchlick Branch,Main      ,3447
560.0743
River Rch & RM=Birchlick Branch,Main      ,2695.5
597.5531
River Rch & RM=Birchlick Branch,Main      ,2382.5
642.4336
River Rch & RM=Birchlick Branch,Main      ,289
702.4839
Boundary for River Rch & Prof#=Birchlick Branch,Main      ,1
Up Type=0
Dn Type=3
Dn Slope=0.027576

--- Birchlick Branch.g01 (geometry) ---

Geom Title=Geometry
Program Version=4.00

River Reach=Birchlick Branch,Main
Reach XY= 30
     1721422.901      136401.041     1721357.882      136461.093
     1721310.325      136483.148      1721260.01      136492.108
     1721218.656      136487.973      1721118.18       136439.41
     1721045.066      136448.504     1721015.196      136497.978
     1720820.646      136575.642     1720664.204      136712.639
      1720514.03       136761.25     1720081.892      136751.479
     1719995.769      136739.591     1719972.342      136725.535
      1719952.56      136697.423     1719903.033      136597.178
     1719815.348      136542.567     1719785.664      136534.966
     1719694.157       136536.92     1719620.693      136575.378
      1719579.46      136576.463     1719299.512      136527.635
     1719221.443      136524.203      1719035.84      136475.551
     1718957.715      136472.296     1718865.484      136484.232
     1718789.319      136510.361     1718654.971      136620.099
     1718473.116      136825.178     1718388.136      136866.819

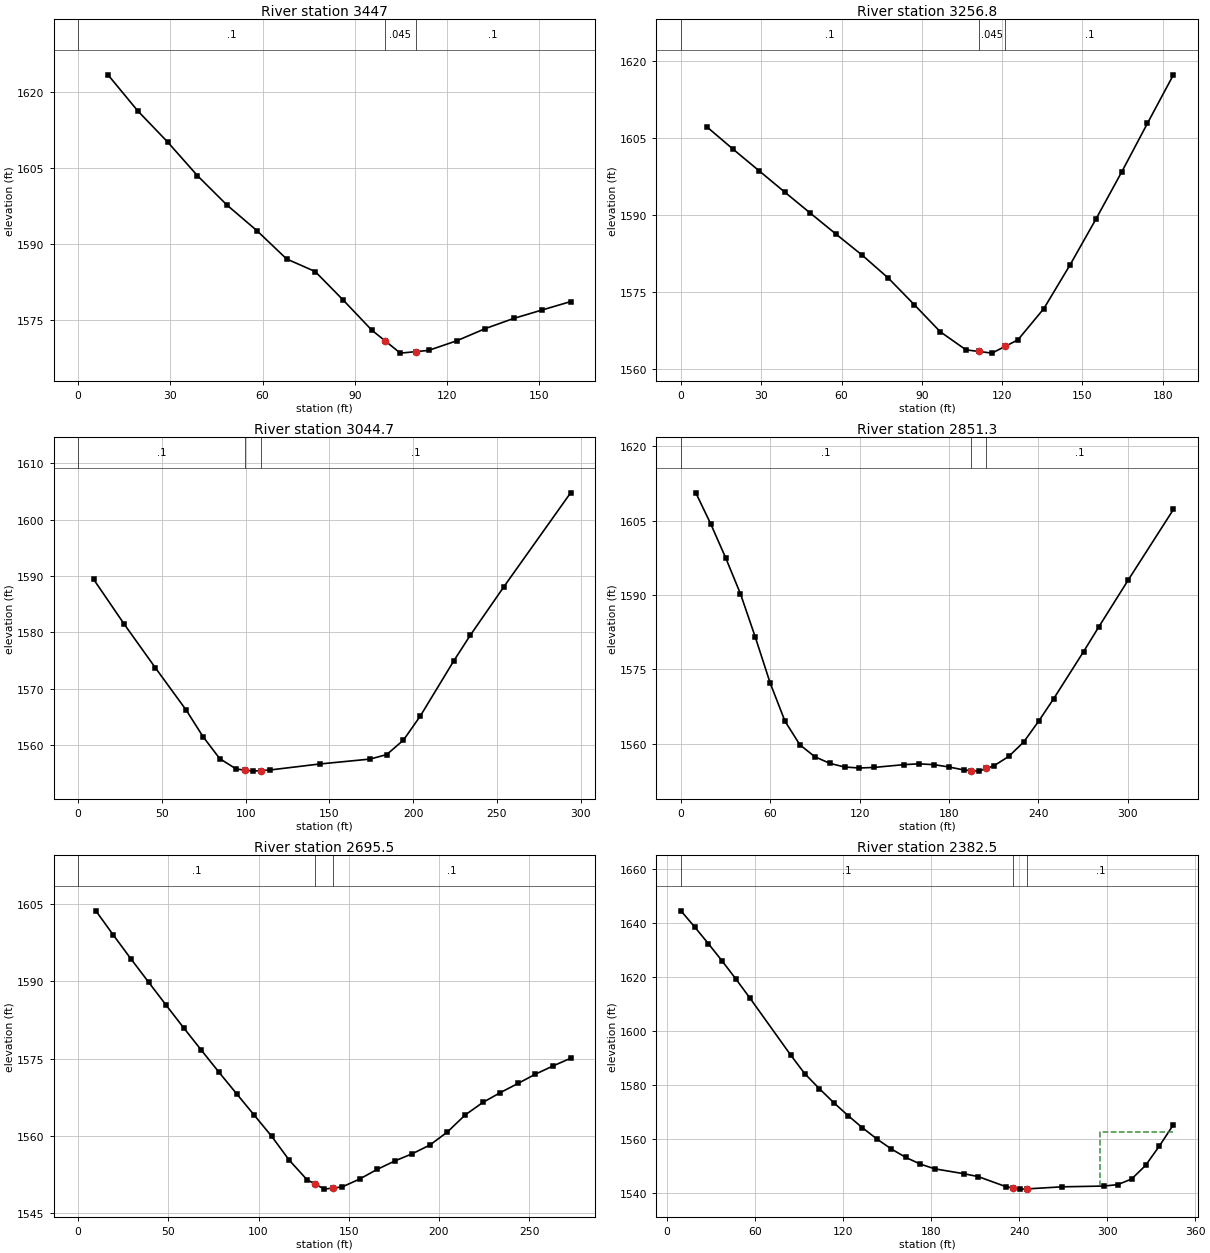
Type RM Length L Ch R = 1 ,3447    ,173,190.2,207.4
XS GIS Cut Line= 3
     1721358.571      136314.286     1721387.519      136375.628
     1721457.132       136436.28
#Sta/Elev= 19
     9.7 1623.35    19.4 1616.22    29.1 1610.08    38.8 1603.43    48.4 1597.63
    58.1 1592.59    67.8 1586.98    77.1 1584.49    86.3  1578.8    95.5 1572.92
    99.8 1570.82   104.8 1568.37   109.8 1568.66     114 1568.91   123.2 1570.82
   132.5 1573.23   141.7 1575.23   150.9 1576.89   160.2 1578.55
#Mann= 3 , 0 , 0
       0      .1       0    99.8    .045       0   109.8      .1       0
Bank Sta=99.8,109.8
XS Rating Curve= 0 ,0
Exp/Cntr=0.3,0.1

Type RM Length L Ch R = 1 ,3256.8  ,211.5,212.1,212.8
XS GIS Cut Line= 2
     1721258.632      136380.452     1721257.943      136564.478
#Sta/Elev= 21
     9.7 1607.26    19.4 1602.95    29.1 1598.75    38.7 1594.59    48.4 1590.43
    58.1  1586.3    67.8 1582.23    77.5 1577.79    87.2 1572.61    96.9 1567.34
   106.5 1563.82   111.2 1563.51   116.2 1563.18   121.2 1564.51   125.9 1565.76
   135.6 1571.86   145.3 1580.29     155 1589.24   164.7 1598.49   174.3 1607.95
     184  1617.4
#Mann= 3 , 0 , 0
       0      .1       0   111.2    .045       0   121.2      .1       0
Bank Sta=111.2,121.2
XS Rating Curve= 0 ,0
Exp/Cntr=0.3,0.1

Type RM Length L Ch R = 1 ,3044.7  ,207.1,193.4,179.3
XS GIS Cut Line= 3
     1721063.259       136324.15     1721061.032      136388.612
     1721053.961      136618.021
#Sta/Elev= 20
     9.2 1589.44    27.6 1581.42    46.1 1573.72    64.5 1566.21    74.5 1561.52
    84.5  1557.6    94.4 1555.75    99.4 1555.57   104.4 1555.38   109.4 1555.48
   114.4 1555.58   144.3 1556.65   174.3 1557.52   184.2 1558.32   194.2 1560.89
   204.2 1565.13   224.2 1574.93   234.1  1579.5   254.1 1588.09     294 1604.78
#Mann= 3 , 0 , 0
       0      .1       0    99.4    .045       0   109.4      .1       0
Bank Sta=99.4,109.4
XS Rating Curve= 0 ,0
Exp/Cntr=0.3,0.1

Type RM Length L Ch R = 1 ,2851.3  ,158,155.8,153.6
XS GIS Cut Line= 3
      1720795.28       136390.59     1720882.954      136512.118
     1720988.857       136658.82
#Sta/Elev= 30
      10 1610.62      20 1604.36      30 1597.55      40 1590.25      50 1581.48
    59.9 1572.31    69.9 1564.57    79.9 1559.82    89.9 1557.42    99.9 1556.09
   109.9 1555.34   119.9 1555.14   129.9 1555.26   149.9 1555.82   159.9 1555.98
     170 1555.81     180 1555.35   190.1 1554.74   195.1 1554.62   200.1 1554.51
   205.1 1555.04   210.2 1555.58   220.2 1557.47   230.3  1560.4   240.3 1564.58
   250.4 1569.12   270.5 1578.62   280.5  1583.5   300.6 1593.11   330.8 1607.26
#Mann= 3 , 0 , 0
       0      .1       0   195.1    .045       0   205.1      .1       0
Bank Sta=195.1,205.1
XS Rating Curve= 0 ,0
Exp/Cntr=0.3,0.1

Type RM Length L Ch R = 1 ,2695.5  ,299.4,313.1,326.7
XS GIS Cut Line= 3
     1720674.263      136513.127     1720766.561      136613.691
      1720858.86      136714.256
#Sta/Elev= 30
     9.8  1603.7    19.5    1599    29.2  1594.4      39 1589.88    48.8 1585.38
    58.5 1580.99    68.3 1576.66      78 1572.41    87.8 1568.22    97.5  1564.1
   107.3 1559.94     117 1555.32   126.8 1551.55   131.5 1550.65   136.5  1549.7
   141.5 1549.92   146.3 1550.12     156 1551.65   165.7 1553.52   175.5 1555.16
   185.3 1556.58     195 1558.26   204.7 1560.79   214.5 1564.08   224.3 1566.51
     234 1568.42   243.8  1570.2   253.5 1572.01   263.3 1573.61     273 1575.09
#Mann= 3 , 0 , 0
       0      .1       0   131.5    .045       0   141.5      .1       0
Bank Sta=131.5,141.5
XS Rating Curve= 0 ,0
Exp/Cntr=0.3,0.1

Type RM Length L Ch R = 1 ,2382.5  ,299.7,301.8,303.9
XS GIS Cut Line= 4
     1720486.815      136517.428     1720480.028      136610.983
     1720501.009      136727.396      1720509.69      136860.208
#Sta/Elev= 30
     9.4 1644.64    18.8 1638.64    28.1 1632.47    37.5 1626.03    46.9 1619.33
    56.3 1612.38    84.4 1591.02    93.8 1584.24   103.7 1578.71   113.5 1573.52
   123.4 1568.66   133.2 1564.13   143.1 1559.97   152.9 1556.27   162.8 1553.14
   172.7 1550.66   182.5 1548.92   202.2 1547.12   212.1 1546.04   231.1 1542.29
   235.6 1541.86   240.6 1541.39   245.6 1541.48   269.1 1542.24   297.7 1542.53
   307.2 1543.05   316.7 1545.14   326.2 1550.17   335.7 1557.43   345.2  1565.3
#Mann= 3 , 0 , 0
     9.4      .1       0   235.6    .045       0   245.6      .1       0
#XS Ineff= 2 , 0
                          295.39         1562.58
Permanent Ineff=
       F       F
Bank Sta=235.6,245.6
XS Rating Curve= 0 ,0
Exp/Cntr=0.3,0.1

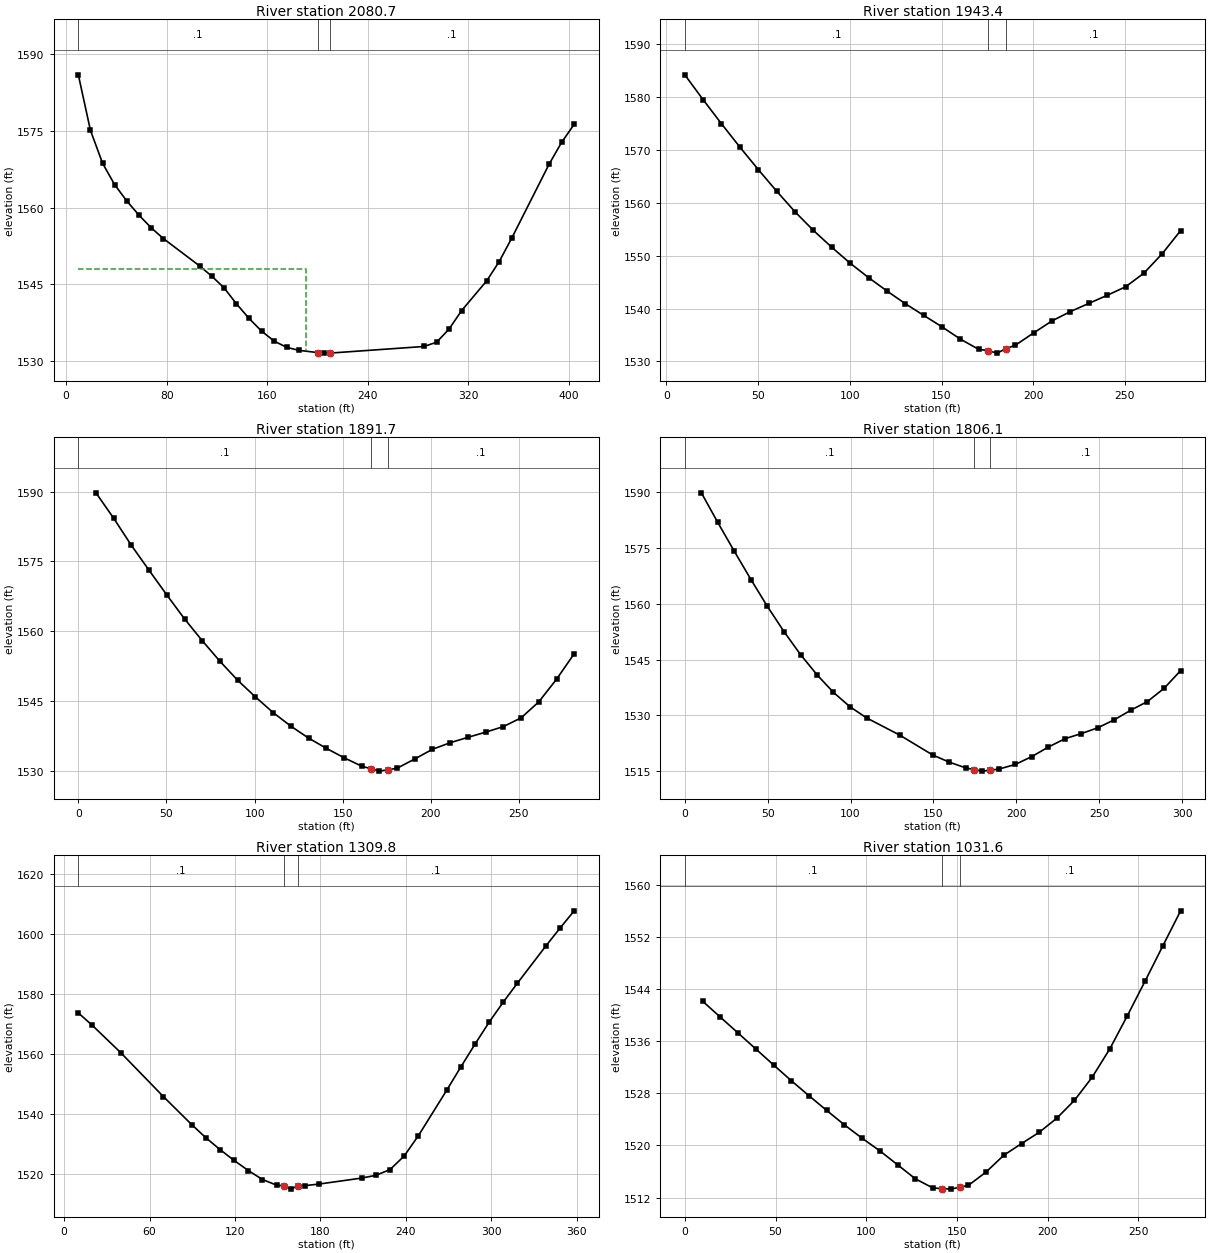
Type RM Length L Ch R = 1 ,2080.7  ,131.5,137.2,142.9
XS GIS Cut Line= 3
     1720242.675      136503.865     1720206.856      136624.211
     1720195.857      136902.523
#Sta/Elev= 30
     9.7  1585.9    19.3 1575.09      29 1568.63    38.6 1564.45    48.3 1561.26
      58 1558.49    67.6 1556.06    77.3 1553.95   106.2 1548.59   115.9 1546.59
   125.6 1544.33   135.5  1541.2   145.5 1538.35   155.4 1535.89   165.4 1533.94
   175.3 1532.72   185.2 1532.12   200.1 1531.69   205.1 1531.58   210.1 1531.59
   284.7 1532.88   294.7 1533.71   304.6 1536.28   314.6 1539.89   334.5 1545.68
   344.4 1549.42   354.4    1554   384.2 1568.47   394.1 1572.71   404.1 1576.24
#Mann= 3 , 0 , 0
     9.7      .1       0   200.1    .045       0   210.1      .1       0
#XS Ineff= 2 , 0
          190.44 1547.93
Permanent Ineff=
       F       F
Bank Sta=200.1,210.1
XS Rating Curve= 0 ,0
Exp/Cntr=0.3,0.1

Type RM Length L Ch R = 1 ,1943.4  ,50.4,51.7,53.1
XS GIS Cut Line= 2
     1720118.909       136586.94     1720030.747      136853.121
#Sta/Elev= 30
      10 1584.25      20 1579.54      30 1574.99    40.1 1570.54    50.1  1566.3
    60.1 1562.22    70.1 1558.32    80.1  1554.8    90.1 1551.62   100.1 1548.61
   110.2 1545.86   120.2 1543.34   130.2 1540.93   140.2 1538.73   150.2 1536.55
   160.2 1534.23   170.2 1532.29   175.3 1532.04   180.3 1531.56   185.3 1532.43
   190.3 1533.06   200.3  1535.4   210.3 1537.67   220.3 1539.43   230.3 1540.97
   240.3  1542.5   250.4 1544.12   260.4 1546.71   270.4  1550.4   280.4 1554.76
#Mann= 3 , 0 , 0
      10      .1       0   175.3    .045       0   185.3      .1       0
Bank Sta=175.3,185.3
XS Rating Curve= 0 ,0
Exp/Cntr=0.3,0.1

Type RM Length L Ch R = 1 ,1891.7  ,79.4,85.6,91.9
XS GIS Cut Line= 2
     1720077.142        136588.2     1719970.569      136848.562
#Sta/Elev= 30
      10 1589.78    20.1 1584.28    30.1 1578.47    40.2 1573.07    50.2  1567.8
    60.3 1562.61    70.3 1557.95    80.4 1553.49    90.4 1549.43   100.5 1545.83
   110.5 1542.48   120.6 1539.54   130.6 1536.99   140.7 1534.78   150.7 1532.76
   160.8 1530.93   165.8  1530.4   170.8 1529.87   175.8 1530.18   180.9  1530.5
   190.9  1532.5   200.9 1534.57     211 1535.99     221 1537.14   231.1 1538.26
   241.1 1539.45   251.2 1541.34   261.2 1544.77   271.3 1549.65   281.3 1555.13
#Mann= 3 , 0 , 0
       0      .1       0   165.8    .045       0   175.8      .1       0
Bank Sta=165.8,175.8
XS Rating Curve= 0 ,0
Exp/Cntr=0.3,0.1

Type RM Length L Ch R = 1 ,1806.1  ,504.5,496.3,488.1
XS GIS Cut Line= 2
     1720056.891      136571.037     1719859.408      136795.647
#Sta/Elev= 30
      10 1589.85    19.9 1581.88    29.9 1574.11    39.9 1566.54    49.8 1559.33
    59.8 1552.56    69.8 1546.36    79.8  1540.9    89.7 1536.18    99.7 1532.31
   109.7 1529.32   129.6 1524.72   149.5 1519.37   159.5 1517.44   169.5 1515.88
   174.4 1515.45   179.4 1515.02   184.4 1515.29   189.4 1515.56   199.4 1516.82
   209.4 1518.95   219.3 1521.49   229.3 1523.73   239.3 1525.13   249.2 1526.68
   259.2 1528.86   269.2 1531.44   279.1 1533.74   289.1 1537.27   299.1 1542.05
#Mann= 3 , 0 , 0
       0      .1       0   174.4    .045       0   184.4      .1       0
Bank Sta=174.4,184.4
XS Rating Curve= 0 ,0
Exp/Cntr=0.3,0.1

Type RM Length L Ch R = 1 ,1309.8  ,284.7,278.2,271.3
XS GIS Cut Line= 2
     1719588.141      136422.383     1719477.463      136763.095
#Sta/Elev= 30
      10 1573.64    19.9 1569.46    39.8  1560.4    69.7 1545.81    89.6 1536.48
    99.5 1532.12   109.5 1528.17   119.4 1524.54   129.4 1521.18   139.3  1518.2
   149.3 1516.31   154.2 1516.15   159.2    1515   164.2 1516.07   169.2 1516.17
   179.1 1516.69     209 1518.68   218.9 1519.58   228.9 1521.51   238.8 1526.01
   248.8 1532.77   268.7 1547.91   278.6 1555.64   288.6 1563.27   298.5 1570.56
   308.5 1577.29   318.4 1583.57   338.3  1595.9   348.3 1601.86   358.2 1607.61
#Mann= 3 , 0 , 0
      10      .1       0   154.2    .045       0   164.2      .1       0
Bank Sta=154.2,164.2
XS Rating Curve= 0 ,0
Exp/Cntr=0.3,0.1

Type RM Length L Ch R = 1 ,1031.6  ,393.7,387.3,381.2
XS GIS Cut Line= 3
     1719269.838      136376.095     1719265.399       136512.85
     1719269.531      136649.229
#Sta/Elev= 30
     9.8 1542.12    19.5 1539.69    29.3 1537.25    39.1  1534.8    48.9 1532.35
    58.6 1529.95    68.4 1527.63    78.2 1525.37      88 1523.15    97.7 1521.11
   107.5 1519.17   117.3 1517.03   127.1 1514.88   136.8 1513.47   141.6 1513.39
   146.6  1513.3   151.6  1513.6   156.3 1513.87   166.1 1515.93   175.8 1518.49
   185.6 1520.28   195.3    1522     205 1524.16   214.8 1526.92   224.5 1530.44
   234.3 1534.82     244 1539.92   253.8 1545.24   263.5  1550.6   273.3 1555.97
#Mann= 3 , 0 , 0
       0      .1       0   141.6    .045       0   151.6      .1       0
Bank Sta=141.6,151.6
XS Rating Curve= 0 ,0
Exp/Cntr=0.3,0.1

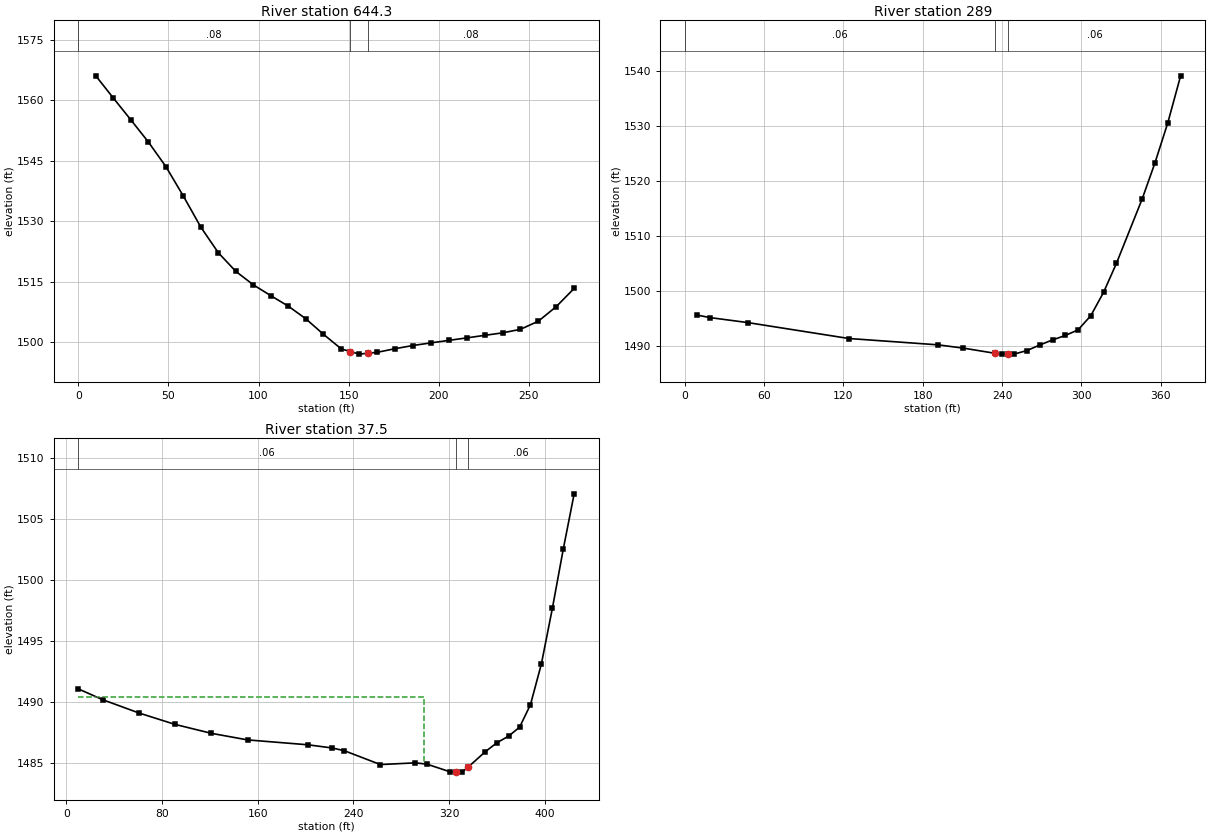
Type RM Length L Ch R = 1 ,644.3   ,365.4,355.3,345.2
XS GIS Cut Line= 3
     1718811.585      136338.261     1718877.838       136457.06
     1718922.886      136588.766
#Sta/Elev= 30
     9.7  1566.1    19.4  1560.6    29.1  1555.2    38.9 1549.66    48.6 1543.57
    58.3 1536.25      68 1528.54    77.7 1522.19    87.4 1517.57    97.2 1514.21
   106.9 1511.52   116.6 1508.92   126.3 1505.79     136 1501.97     146 1498.31
   150.9 1497.68   155.9 1497.03   160.9 1497.26   165.9 1497.48   175.8 1498.38
   185.7 1499.17   195.7 1499.82   205.6 1500.44   215.6 1501.06   225.5 1501.69
   235.5 1502.31   245.4 1503.19   255.3  1505.2   265.3 1508.84   275.2 1513.34
#Mann= 3 , 0 , 0
       0     .08       0   150.9    .045       0   160.9     .08       0
Bank Sta=150.9,160.9
XS Rating Curve= 0 ,0
Exp/Cntr=0.3,0.1

Type RM Length L Ch R = 1 ,289     ,243,251.6,260.1
XS GIS Cut Line= 4
     1718496.561      136475.551     1718512.085      136598.685
     1718647.385      136721.862     1718702.212      136762.148
#Sta/Elev= 22
     9.5 1495.54    19.1 1495.09    47.7 1494.18   124.1 1491.29   191.5 1490.14
   210.8 1489.54   234.7  1488.6   239.7 1488.45   244.7 1488.46   249.3 1488.47
   258.9  1489.1   268.6 1490.12   278.2 1491.03   287.8 1491.84   297.5 1492.86
   307.1 1495.42   316.8 1499.68   326.5 1504.93     346 1516.65   355.7 1523.23
   365.4  1530.5   375.1 1539.04
#Mann= 3 , 0 , 0
       0     .06       0   234.7    .045       0   244.7     .06       0
Bank Sta=234.7,244.7
XS Rating Curve= 0 ,0
Exp/Cntr=0.3,0.1

Type RM Length L Ch R = 1 ,37.5    ,35.9,37.5,39
XS GIS Cut Line= 4
     1718390.224       136533.06     1718398.057      136795.477
     1718440.442      136893.812      1718490.05      136917.175
#Sta/Elev= 25
    10.1  1491.1    30.3 1490.22    60.6 1489.13    90.9 1488.19   121.2 1487.46
   151.5 1486.92   201.9 1486.52   222.1 1486.26   232.2 1486.04   262.5  1484.9
   291.7 1485.04   301.5 1484.93   320.9  1484.3   325.7 1484.29   330.7 1484.28
   335.7 1484.68   350.1 1485.95   359.9 1486.69   369.6 1487.23   378.8 1487.96
   387.9 1489.81     397 1493.14   406.2  1497.7   415.3 1502.55   424.4 1507.08
#Mann= 3 , 0 , 0
    10.1     .06       0   325.7    .045       0   335.7     .06       0
#XS Ineff= 2 , 0
          298.66 1490.41
Permanent Ineff=
       F       F
Bank Sta=325.7,335.7
XS Rating Curve= 0 ,0
Exp/Cntr=0.3,0.1

Chan Stop Cuts=-1
Use User Specified Reach Order=0